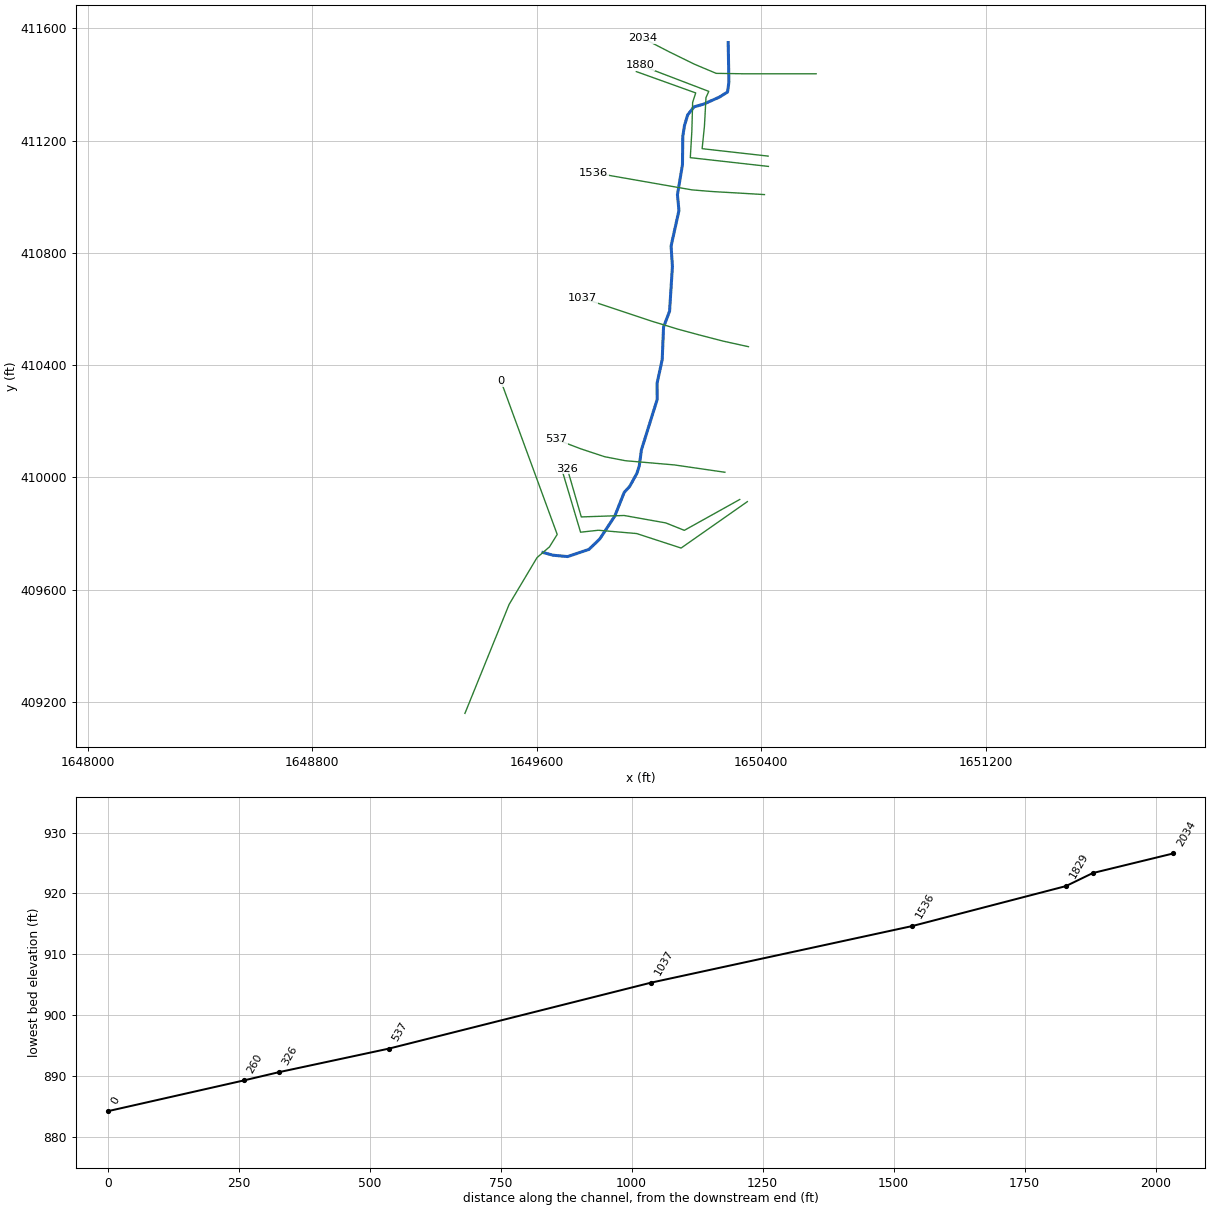
--- HONEYRN2.prj (project) ---

Proj Title=HONEYRN2
Current Plan=p01
Default Exp/Contr=0,0
English Units
Geom File=g01
Flow File=f01
Plan File=p01
BEGIN DESCRIPTION:
---------- MODELED AS PART OF WVEMD CTP PROGRAM, 2023----------
Stream Name: Honey Run II
Flood Zone:  AFH
Wetzel County, WV
HEC-RAS Version: RAS 6.3
Vertical Datum: NAVD88
Projection: NAD 1983 StatePlane West Virginia S FIPS 4702 (US Feet)
Terrain: 1-meter West Virginia FEMA R3 South Central (collected 2018-2020)
Land Use: 2019 NLCD
Hydrologic Method:
WV SIR2010-5033 regression equations
Additional Model Notes:
Leveraged XS. KWSE used, as  tie-in was not achieved with normal depth
END DESCRIPTION:
DSS Export Rating Curves= 0
DSS Export Rating Curve Sorted= 0
DSS Export Volume Flow Curves= 0
DXF OffsetX= 0
DXF OffsetY= 0
DXF ScaleX= 0
DXF ScaleY= 0

--- HONEYRN2.p01 (plan) ---

Plan Title=Floodplain
Program Version=6.30
Short Identifier=Floodplain
Geom File=g01
Flow File=f01
Subcritical Flow
K Sum by GR= 0
Std Step Tol= 0.01
Critical Tol= 0.01
Num of Std Step Trials= 20
Max Error Tol= 0.3
Flow Tol Ratio= 0.001
Split Flow NTrial= 30
Split Flow Tol= 0.02
Split Flow Ratio= 0.02
Log Output Level= 0
Friction Slope Method= 1
Unsteady Friction Slope Method= 2
Unsteady Bridges Friction Slope Method= 1
Parabolic Critical Depth
Global Vel Dist= 0 , 0 , 0
Global Log Level= 0
CheckData=True
Encroach Param=-1 ,0,0, 0
Mapping Interval=1HOUR
Computation Time Step Use Courant=        0
Computation Time Step Use Time Series=    0
Computation Time Step Count To Double=0
Computation Time Step Max Doubling=0
Computation Time Step Max Halving=0
Computation Time Step Residence Courant=0
Run HTab= 0
Run UNet= 0
Run Sediment= 0
Run PostProcess= 0
Run WQNet= 0
Run RASMapper= 0
UNET Theta= 0
UNET Theta Warmup= 0
UNET ZTol= 0
UNET ZSATol= 0
UNET MxIter= 0
UNET Max Iter WO Improvement= 0
UNET MaxInSteps= 0
UNET DtIC= 0
UNET DtMin= 0
UNET MaxCRTS= 0
UNET WFStab= 0
UNET SFStab= 0
UNET WFX= 1
UNET SFX= 1
UNET Gravity=32.17405
UNET 1D Methodology=Finite Difference
UNET DSS MLevel= 1
UNET Pardiso=0
UNET DZMax Abort= 0
UNET Use Existing IB Tables= 0
UNET Froude Reduction=False
UNET Froude Limit= 0
UNET Froude Power= 0
UNET D1 Cores= 0
UNET WindReference=Eulerian
UNET WindDragFormulation=Hsu (1988)
UNET D2 Coriolis=0
UNET D2 Cores= 0
UNET D2 Theta= 1
UNET D2 Theta Warmup= 1
UNET D2 Z Tol= 0.01
UNET D2 Volume Tol= 0.01
UNET D2 Max Iterations= 20
UNET D2 Equation= 0
UNET D2 RampUpFraction=0.1
UNET D2 TimeSlices= 1
UNET D2 Turbulence Formulation=Non-Conservative (original)
UNET D2 Eddy Viscosity=0.3
UNET D2 Transverse Eddy Viscosity=0.1
UNET D2 Smagorinsky Mixing=0
UNET D2 BCVolumeCheck=0
UNET D2 Cores=0
UNET D2 SolverType=PARDISO (Direct)
UNET D2 Minimum Iterations= 3
UNET D2 Maximum Iterations= 30
UNET D2 Restart Number= 10
UNET D2 Relaxation Coeff=1.3
UNET D2 SOR Precondition Iterations= 10
UNET D2 ILUT Maximum Fill= 8
UNET D2 ILUT Tolerance=1E-08
UNET D2 Convergence Tolerance=0.00001
UNET D1D2 MaxIter= 0
UNET D1D2 ZTol=0.01
UNET D1D2 QTol=0.1
UNET D1D2 MinQTol=1
Write IC File= 0
Write IC File at Fixed DateTime=0
Write IC File at Sim End=0
Echo Input=False
Echo Parameters=False
Echo Output=False
Write Detailed= 0
HDF Write Warmup=0
HDF Write Time Slices=0
HDF Flush=0
HDF Compression= 1
HDF Chunk Size= 1
HDF Spatial Parts= 1
HDF Use Max Rows=0
HDF Fixed Rows= 1
Calibration Method= 0
Calibration Iterations= 20
Calibration Max Change=0.05
Calibration Tolerance=0.2
Calibration Maximum=1.5
Calibration Minimum=0.5
Calibration Optimization Method= 1
WQ AD Non Conservative
WQ ULTIMATE=-1
WQ Max Comp Step=1HOUR
WQ Output Interval=15MIN
WQ Output Selected Increments= 0
WQ Output face flow=0
WQ Output face velocity=0
WQ Output face area=0
WQ Output face dispersion=0
WQ Output cell volume=0
WQ Output cell surface area=0
WQ Output cell continuity=0
WQ Output cumulative cell continuity=0
WQ Output face conc=0
WQ Output face dconc_dx=0
WQ Output face courant=0
WQ Output face peclet=0
WQ Output face adv mass=0
WQ Output face disp mass=0
WQ Output cell mass=0
WQ Output cell source sink temp=0
WQ Output nsm pathways=0
WQ Output nsm derived pathways=0
WQ Create Restart=0
WQ Fixed Restart=0
WQ System Summary=0
WQ Write To DSS=0
Sorting and Armoring Iterations= 10
XS Update Threshold= 0.02
Bed Roughness Predictor= 0
Hydraulics Update Threshold= 0.02
Energy Slope Method= 1
Volume Change Method= 1
Sediment Retention Method= 0
Sediment TS Multiplier= 1
Warm Up Method= 0
XS Weighting Method= 0
Number of US Weighted Cross Sections= 1
Number of DS Weighted Cross Sections= 1
Upstream XS Weight=0
Main XS Weight=1
Downstream XS Weight=0
Number of DS XS's Weighted with US Boundary= 1
Upstream Boundary Weight= 1
Weight of XSs Associated with US Boundary= 0
Number of US XS's Weighted with DS Boundary= 1
Downstream Boundary Weight= 0.5
Weight of XSs Associated with DS Boundary= 0.5
Percentile Method= 0
Sediment Output Level= 3
Mass or Volume Output= 0
Output Increment Type= 1
Profile and TS Output Increment= 1
Transport Output Increment 1
XS Output Flag= 0
XS Output Increment= 10
Read HDF5 Sediment Hotstart= 0
Sediment Hotstart Type= 0
Write Gradation File= 0
Read Gradation Hotstart= 0
Write HDF5 File= 1
Write Binary Output= 1
Write DSS Sediment File= 0
DSS Sediment Output Type= 1
SV Curve= 0
Specific Gage Flag= 0
Subcell Erosion Methods= 0
Subcell Deposition Methods= 0
Advection Scheme= 1
Matrix Solver= 0
Implicit Weighting Factor= 1
Maximum Outer Loop Convergence Iterations= 5
Convergence Maximum Absolute= 0.001
Convergence RMSE= 0.0001
Grain Fractions Max Abs Error= 0.001
Max Subgrid Regions= 1
Max Subgrid Length Scale= 3.402823E+38
Initial Layer Thickness= 3.402823E+38
Min Layer Thickness= 3.402823E+38
Max Layer Thickness= 3.402823E+38
Number of Layers= 5

--- HONEYRN2.f01 (steady flow) ---

Flow Title=Flow
Program Version=6.30
Number of Profiles= 1
Profile Names=F01pct
River Rch & RM=HONEYRN2,Main            ,2034
     586
River Rch & RM=HONEYRN2,Main            ,0
    1590
Boundary for River Rch & Prof#=HONEYRN2,Main            , 1
Up Type= 0
Dn Type= 1
Dn Known WS=889.4
DSS Import GetInterval= 0
DSS Import GetPeak= 0
DSS Import FillOption= 0

--- HONEYRN2.g01 (geometry) ---

Geom Title=Geometry
Program Version=6.31

River Reach=HONEYRN2        ,Main
Reach XY= 30
1650282.83800001411549.5639999961650285.35698507411408.563318984
1650280.49127595411373.3035474461650251.20600002         411355.
1650194.50900002411329.9340000151650161.08600001411320.384000003
1650138.40700001411291.7370000031650127.06800002411253.541000009
1650121.10000001      411215.941     1650119.906411114.481000006
     1650102.001411007.650000006     1650107.373410950.953000009
     1650079.322410824.427000001     1650084.097410751.613999993
1650073.95100002410592.2629999971650052.46500002410535.564999998
1650047.69100001410419.7820000051650029.18900001410334.437000006
1650029.78600003410277.739000008     1649973.685410098.096000001
1649965.92600001410040.8009999991649957.57100001410014.541000009
1649931.90700002409967.9889999931649912.21200001409946.503999993
 1649878.5454215 409861.830946981649825.15852619409780.650788546
1649786.88000001409743.585000008     1649710.487409717.921000019
1649658.68742716409722.7382672431649622.91041481409732.565237597

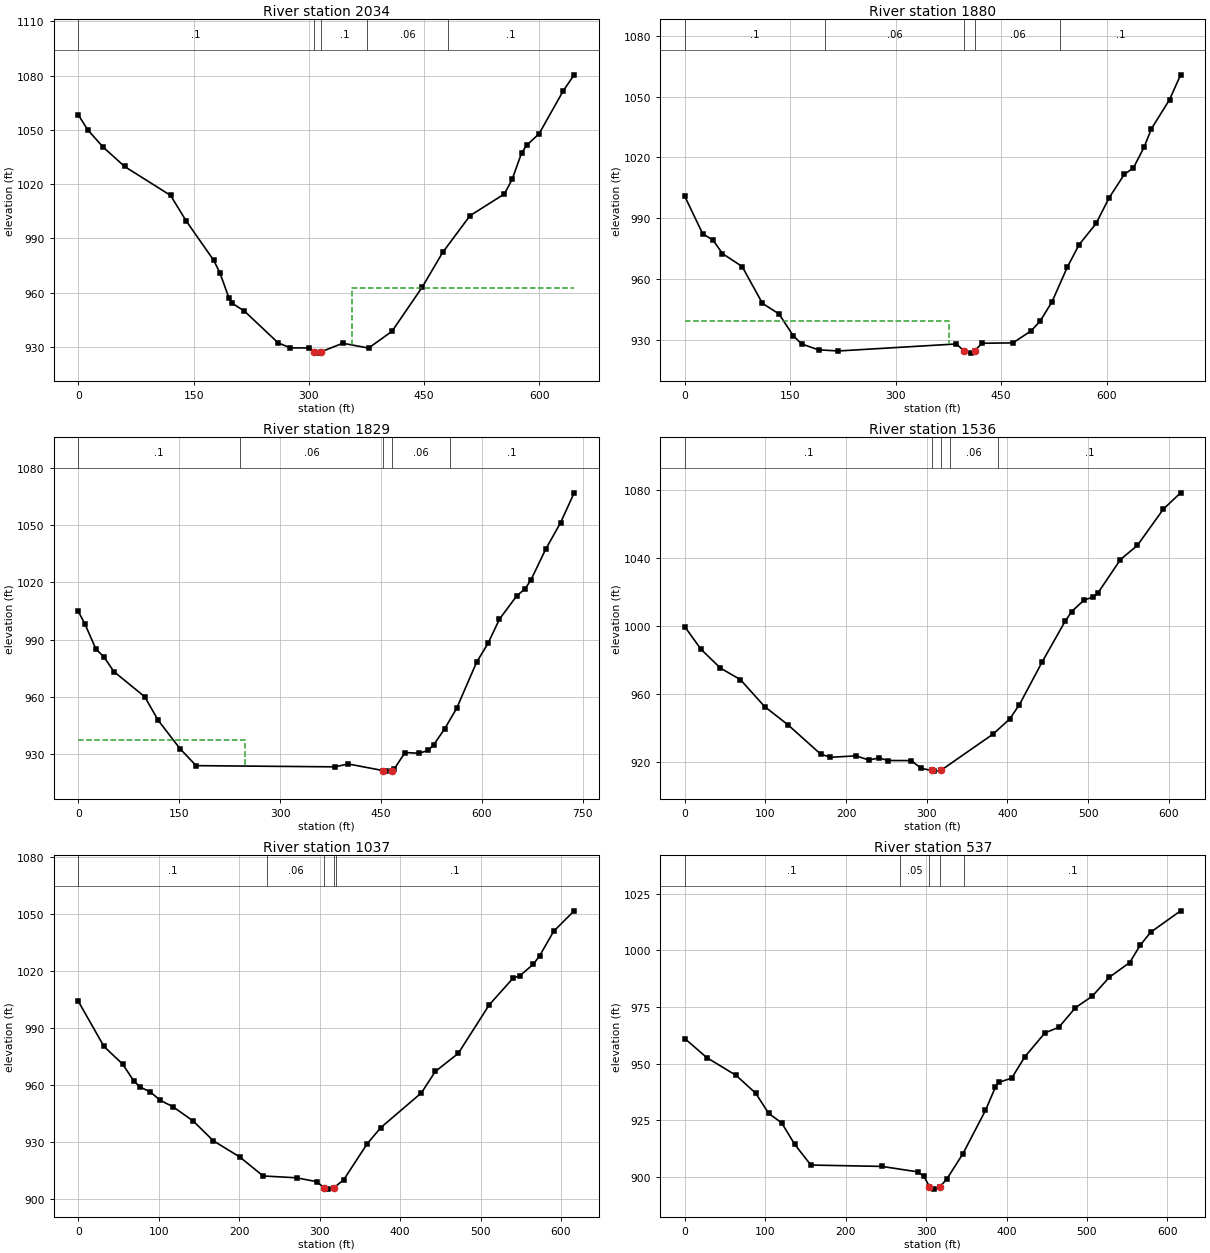
Type RM Length L Ch R = 1 ,2034    ,161.5,153.9,141.6
BEGIN DESCRIPTION:
Structure 2 XS 4
END DESCRIPTION:
XS GIS Cut Line= 6
 1650596.2498565411438.2387732571650340.00004092411438.238773257
1650239.99991284411439.7715785951650162.33930701411472.490017086
1650072.19644268411516.7287737581649979.49584067411564.575134754
#Sta/Elev= 30
       0 1058.32    12.1 1050.09    32.1 1040.58    60.1  1029.8   120.1 1013.76
   140.1  999.83   176.1  977.95   184.1  971.14   196.1  956.97   200.1  954.15
   216.1  949.84   260.1  932.22   276.1  929.48   300.1  929.43  306.24927.4038
   312.1  926.57   316.1  927.34   344.1  932.02   377.8  929.38   408.2  938.62
   447.5  963.03   474.2  982.26   509.8 1002.59   554.5 1014.57   564.6 1022.67
     577 1037.38   584.1  1041.8   599.6 1047.83   631.1 1071.61   645.3 1080.46
#Mann= 5 ,-1,0
       0      .1       0  306.24    .045       0   316.1      .1       0
  376.26     .06       0  480.53      .1       0
#XS Ineff= 2 , 0
                          356.79          962.52
Permanent Ineff=
       F       F
Bank Sta=306.24,316.1
XS Rating Curve= 0 ,0
Exp/Cntr(USF)=0,0
Exp/Cntr=0.3,0.1

Type RM Length L Ch R = 1 ,1880    ,50,51.5,52.3
BEGIN DESCRIPTION:
Structure 2 XS 3
END DESCRIPTION:
XS GIS Cut Line= 6
1650425.24359935411144.8497670011650189.97737534411171.397317571
1650198.21627034411251.9554020591650203.70886701411353.568440447
1650213.77862757411375.5388271261649969.35807577 411468.91297051
#Sta/Elev= 30
       0 1000.77    25.3   982.4    40.5  978.99    53.5  972.54    81.6   966.1
   110.5  947.91     134  942.72   154.1  932.03   166.2  927.87   190.3  924.96
   218.5  924.41   386.4  927.87  396.98924.4973   406.5  923.34   412.5  924.53
   422.8  928.22   466.9   928.4   492.6  934.32   505.4  939.05   522.6  948.82
     544  965.68   561.1  976.97   585.2  987.38   603.4  999.89   625.3 1011.65
   638.2 1014.79   653.4 1025.03   663.9 1034.21   689.6 1048.51   705.4  1060.8
#Mann= 5 ,-1,0
       0      .1       0     200     .06       0  396.98    .045       0
   412.5     .06       0  533.71      .1       0
#XS Ineff= 2 , 0
          376.21  939.41
Permanent Ineff=
       F       F
Bank Sta=396.98,412.5
XS Rating Curve= 0 ,0
Exp/Cntr(USF)=0,0
Exp/Cntr=0.3,0.1

Type RM Length L Ch R = 1 ,1829    ,288.2,292.9,302.8
BEGIN DESCRIPTION:
Structure 2 XS 2
END DESCRIPTION:
XS GIS Cut Line= 6
1650426.15903213 411108.232455871650147.86746753411139.357170331
 1650153.3600642411234.5621792721650156.10636254 411336.17521766
1650167.09155588411370.046230456 1649955.6265841411446.027151053
#Sta/Elev= 30
       0 1004.75    10.1  997.94    26.2     985    38.3  980.86    52.8  973.28
    98.7  960.12   118.8  947.76     151  933.02   175.1  924.06   381.4  923.43
   401.4  924.93   453.4  921.47   457.4  921.19  465.99921.4636   469.4  922.12
   485.9  930.93   506.9  930.54   520.1     932   528.6  935.01   545.1  943.48
   562.6  954.02   592.3  978.15   609.3  988.04   626.3 1000.71   651.8 1012.76
   664.6 1016.66   673.1 1021.19   695.2 1037.39   717.1  1051.1   737.4 1066.79
#Mann= 5 ,-1,0
       0      .1       0     240     .06       0   453.4    .045       0
  465.99     .06       0  552.67      .1       0
#XS Ineff= 2 , 0
          247.58  937.65
Permanent Ineff=
       F       F
Bank Sta=453.4,465.99
XS Rating Curve= 0 ,0
Exp/Cntr(USF)=0,0
Exp/Cntr=0.3,0.1

Type RM Length L Ch R = 1 ,1536    ,499.2,498.7,497.4
BEGIN DESCRIPTION:
Structure 2 XS 1
END DESCRIPTION:
XS GIS Cut Line= 6
1650412.08913559411007.7757234281650317.51124075411013.394806668
1650229.22401576411018.4348228421650154.08374609411024.502396002
1650055.58066225411041.7402224241649803.16679701411085.913034335
#Sta/Elev= 30
       0  999.42      20  986.23    44.1  975.15    68.8  968.41      99  952.54
   128.2  941.71   168.3   924.7   180.3  922.75   212.1   923.6   228.4  921.15
   240.5  922.35   252.5  920.87   280.9  920.81     293  916.25  306.44  915.02
   309.3  914.63   317.4  915.02   382.4  936.44   402.7  945.16   414.9  953.65
   443.3   978.9   471.7 1002.73   479.8 1008.36   495.3 1015.19   505.7 1016.67
     512 1019.05   540.2 1038.88   561.1 1047.13   593.5 1068.56   614.8 1078.05
#Mann= 5 ,-1,0
       0      .1       0  306.44    .045       0   317.4      .1       0
  328.56     .06       0  388.56      .1       0
Bank Sta=306.44,317.4
XS Rating Curve= 0 ,0
Exp/Cntr(USF)=0,0
Exp/Cntr=0.3,0.1

Type RM Length L Ch R = 1 ,1037    ,499.2,500.1,501.6
XS GIS Cut Line= 6
1650355.10959075410465.7367812541650262.24724367410486.293498665
1650176.27267809 410508.612679751650102.89618443410528.507653087
1650007.14637592410557.7228177491649764.04646842410638.756448343
#Sta/Elev= 30
       0 1004.19    31.8  980.45    55.2  971.06    68.6  962.48    76.8  958.99
    89.1  956.62   101.4  952.17     118  948.59   142.8  941.16   167.7   930.8
   200.7  922.23   229.7  912.25   271.2  911.28   296.3  909.23  305.87  905.91
   310.3  905.32   317.2  905.91   329.8  910.21   359.1  929.24   375.9  937.68
   426.5  956.02   443.7  967.24   472.2  976.76   510.8 1002.35   540.4 1016.38
   548.8  1017.6   565.7 1023.78   573.4 1028.15   590.9 1041.07   616.3 1051.81
#Mann= 5 ,-1,0
       0      .1       0  233.93     .06       0  305.87    .045       0
   317.2     .06       0  319.96      .1       0
Bank Sta=305.87,317.2
XS Rating Curve= 0 ,0
Exp/Cntr(USF)=0,0
Exp/Cntr=0.3,0.1

Type RM Length L Ch R = 1 ,537     ,210.3,210.8,208.1
BEGIN DESCRIPTION:
Structure 1 XS 4
END DESCRIPTION:
XS GIS Cut Line= 6
1650271.09171417410018.3675972521650091.13800584410044.498778582
1649916.59865676410059.4898903371649842.72675726 410073.72608234
1649758.53499651410101.516381085 1649669.3091251410135.447087511
#Sta/Elev= 30
       0  961.02    27.3  952.62    63.8  944.74    88.2  936.84   104.3  927.94
   120.4  923.78   136.6  914.29   156.7  905.12   245.1  904.52   289.3  902.12
   297.3  900.14  304.11  895.62   309.4  894.48   317.4  895.61   325.7  898.93
   345.5  909.96   373.8  929.28   386.1  939.53   390.1  941.65   406.4  943.52
   422.7  952.97   447.7  963.52   465.1  966.04   485.6  974.66   506.7   979.8
   527.8  988.13   553.1  994.63   566.3 1002.36   579.2 1008.04   616.4 1017.48
#Mann= 5 ,-1,0
       0      .1       0  266.97     .05       0  304.11    .045       0
   317.4     .05       0  346.97      .1       0
Bank Sta=304.11,317.4
XS Rating Curve= 0 ,0
Exp/Cntr(USF)=0,0
Exp/Cntr=0.3,0.1

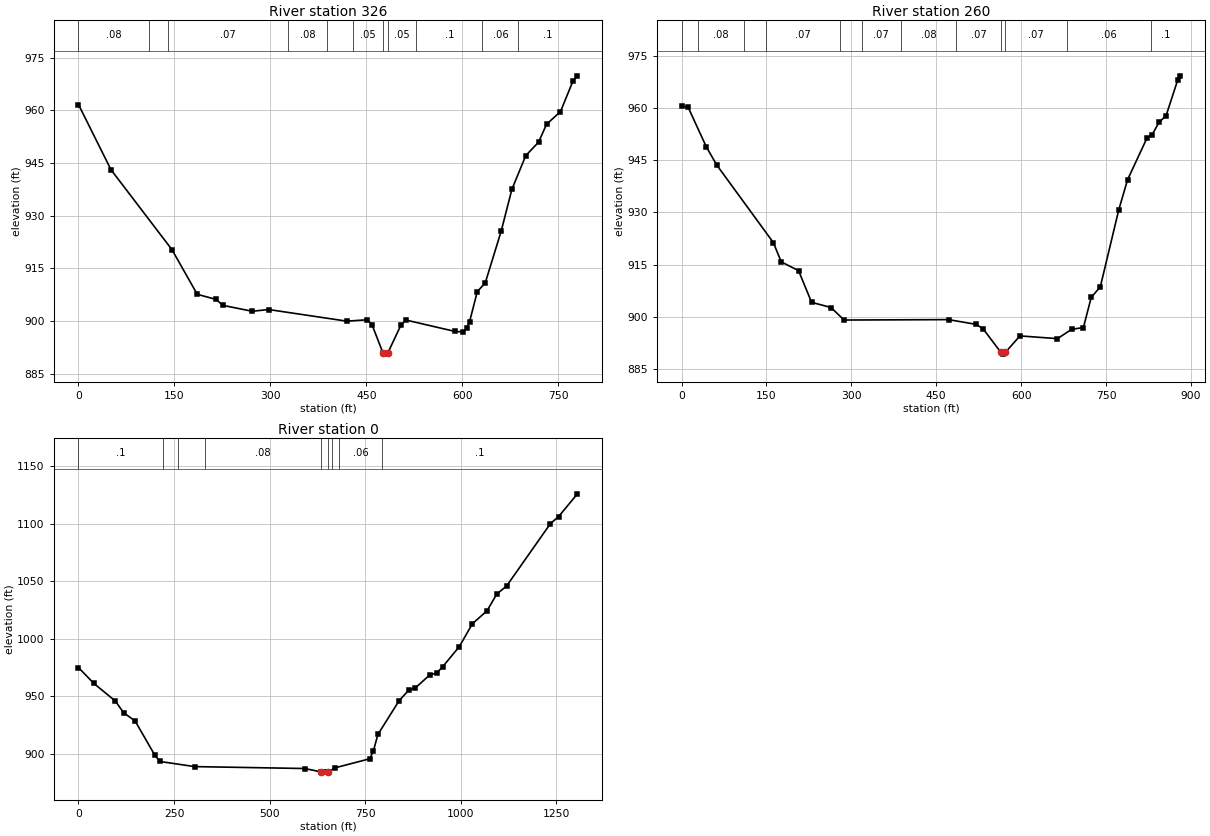
Type RM Length L Ch R = 1 ,326     ,66.5,66.5,66.6
BEGIN DESCRIPTION:
Structure 1 XS 3
END DESCRIPTION:
XS GIS Cut Line= 6
1650323.89718436409921.2674897481650126.57056326409811.415556356
1650060.45597372409837.8613921731649911.95243413409864.307227989
1649759.38030442409859.2214903321649709.64952045410030.958205258
#Sta/Elev= 30
       0  961.68    50.8  943.12   146.2  920.33   185.7  907.63   215.1  906.17
   225.8  904.48   271.6   902.8   297.4  903.29   419.4  899.98   451.8  900.38
   459.2  898.83   475.8  891.05   479.9  890.59   483.9  891.02   503.9  898.77
   511.9   900.3   588.5  897.06   601.8  896.91   606.8  897.96   611.5  899.85
   623.5  908.39     636   910.9     661   925.7   677.6  937.52   699.3  947.13
   719.3  950.95   731.8  956.06   753.6  959.67   773.4  968.51   780.1  969.86
#Mann= 11 ,-1,0
       0     .08       0     110      .1       0     140     .07       0
  327.05     .08       0  388.66      .1       0  428.66     .05       0
   475.8    .045       0   483.9     .05       0   528.3      .1       0
  631.31     .06       0  687.73      .1       0
Bank Sta=475.8,483.9
XS Rating Curve= 0 ,0
Exp/Cntr(USF)=0,0
Exp/Cntr=0.3,0.1

Type RM Length L Ch R = 1 ,260     ,270.7,259.7,241.8
BEGIN DESCRIPTION:
Structure 1 XS 2
END DESCRIPTION:
XS GIS Cut Line= 6
1650351.07019393 409913.653516311650115.08108013409748.288881828
1649956.60663875409799.965330103  1649820.131671409811.711421248
1649756.78976779409804.7539979111649692.34783294410020.874075414
#Sta/Elev= 30
       0  960.46    11.5  960.28    43.8  948.83    62.2  943.61   162.3  921.29
   176.2  915.76   206.8  913.24   229.8  904.14   264.3  902.63   287.2  899.04
   471.8  899.16   520.3  897.81   532.8  896.54   564.3  889.74   568.3  889.24
   572.3  889.74   597.9  894.48   664.2  893.69   689.2  896.36   710.1  896.89
   723.9  905.54     740   908.6   772.7  930.81   788.2   939.4   822.8  951.49
   831.1  952.19   843.7  955.88   856.2  957.79     877  968.18   881.6  969.24
#Mann= 12 ,-1,0
       0      .1       0      30     .08       0     110      .1       0
     150     .07       0     280     .05       0  318.16     .07       0
  387.08     .08       0  485.21     .07       0   564.3    .045       0
   572.3     .07       0   680.4     .06       0  829.25      .1       0
Bank Sta=564.3,572.3
XS Rating Curve= 0 ,0
Exp/Cntr(USF)=0,0
Exp/Cntr=0.3,0.1

Type RM Length L Ch R = 1 ,0       ,110.8,119.4,133.9
XS GIS Cut Line= 6
  1649344.774927409159.1756856451649502.27701496409547.578892854
1649601.67153649409714.2558597271649646.01678456409752.484521854
1649673.54142129409796.8297699211649473.22323174410342.735065093
#Sta/Elev= 30
       0  975.01    40.3   961.2    96.4  945.95     118  935.78   148.2  928.59
     200   898.7     213  893.44   303.6  888.98   592.6  887.31  633.19884.4342
   644.9  884.18   653.4  884.44   671.7  887.96     762  895.78   771.6   902.6
   783.3  916.89   838.7  946.15   864.2  955.48   881.3  957.31   919.6  968.78
   936.7  970.12   952.4  975.55   996.3  993.18  1030.6  1013.1  1068.7 1024.27
  1094.3 1038.85  1119.9 1045.78  1234.9 1100.12  1256.2 1106.19  1305.4 1125.92
#Mann= 9 ,-1,0
       0      .1       0     220     .08       0     260      .1       0
     330     .08       0  633.19    .045       0   653.4     .08       0
  663.19     .07       0  681.73     .06       0  793.93      .1       0
Bank Sta=633.19,653.4
XS Rating Curve= 0 ,0
Exp/Cntr=0.3,0.1
LCMann Table=0

Chan Stop Cuts=-1
Use User Specified Reach Order=0
Composite Channel Slope=5